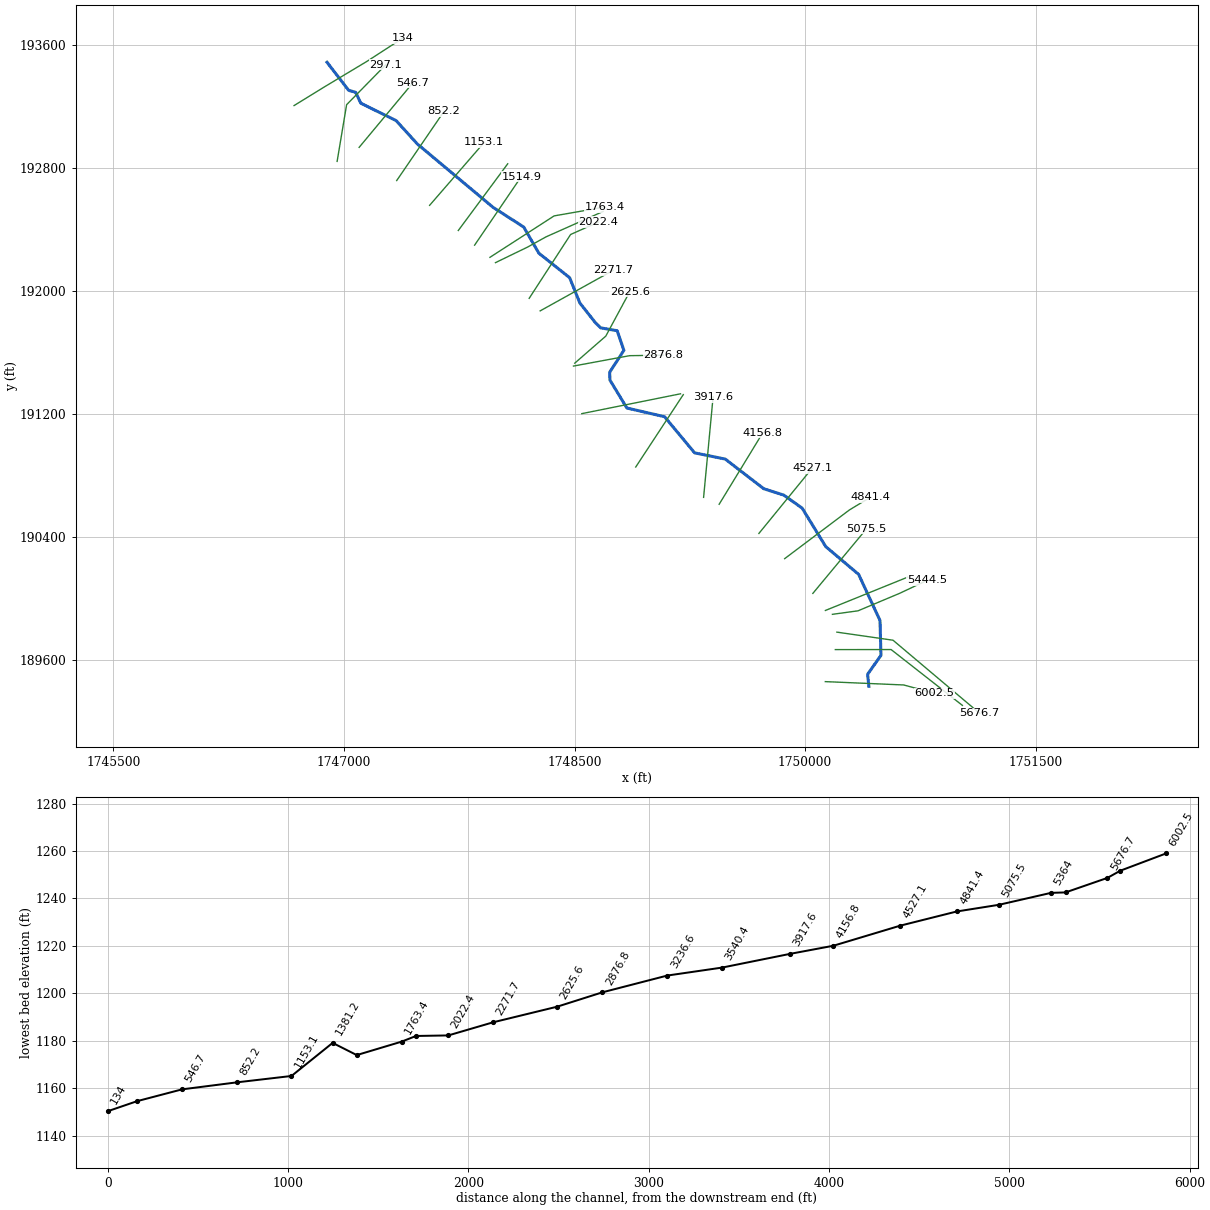
--- SukeCr.prj (project) ---

Proj Title=SukeCr
Current Plan=p01
Default Exp/Contr=0,0
English Units
Geom File=g01
Flow File=f01
Plan File=p01
BEGIN DESCRIPTION:
END DESCRIPTION:
DSS Export Rating Curves= 0
DSS Export Rating Curve Sorted= 0
DSS Export Volume Flow Curves= 0
DXF OffsetX= 0
DXF OffsetY= 0
DXF ScaleX= 0
DXF ScaleY= 0

--- SukeCr.p01 (plan) ---

Plan Title=Floodplain
Program Version=4.00
Geom File=g01
Flow File=f01
K Sum by GR=0
Std Step Tol=0.01
Critical Tol=0.01
Num of Std Step Trials=20
Max Error Tol=0.3
Flow Tol Ratio=0.001
Split Flow NTrial=30
Split Flow Tol=0.02
Split Flow Ratio=0.02
Log Output Level=0
Friction Slope Method=1
Unsteady Friction Slope Method=2
Unsteady Bridges Friction Slope Method=1
Global Log Level=0
CheckData=False
Run HTab=0
Run UNet=0
Run PostProcess=0
UNET Theta=0
UNET Theta Warmup=0
UNET ZTol=0
UNET ZSATol=0
UNET MxIter=0
UNET MaxInSteps=0
UNET DtIC=0
UNET DtMin=0
UNET MaxCRTS=0
UNET WFStab=0
UNET SFStab=0
UNET WFX=0
UNET SFX=0
UNET DSS MLevel=0
UNET DZMax Abort=0
UNET Convert EG Bridges=0
UNET Use Existing IB Tables=0
UNET Froude Limit=0
UNET Froude Power=0
Write IC File=0
Echo Input=False
Echo Output=False
Write Detailed=0

--- SukeCr.f01 (steady flow) ---

Flow Title=NFF Regression Equation
Program Version=4.00
Number of Profiles=1
Profile Names=P100yr
River Rch & RM=SukeCr,Main      ,6002.5
352.3306
River Rch & RM=SukeCr,Main      ,6002.5
554.3658
River Rch & RM=SukeCr,Main      ,5748.8
357.6627
River Rch & RM=SukeCr,Main      ,5748.8
560.4179
River Rch & RM=SukeCr,Main      ,5444.5
505.2688
River Rch & RM=SukeCr,Main      ,5444.5
753.6107
River Rch & RM=SukeCr,Main      ,4841.4
765.4472
River Rch & RM=SukeCr,Main      ,4841.4
512.3671
River Rch & RM=SukeCr,Main      ,4527.1
843.2518
River Rch & RM=SukeCr,Main      ,4527.1
574.8735
River Rch & RM=SukeCr,Main      ,3917.6
849.5332
River Rch & RM=SukeCr,Main      ,3917.6
579.4121
River Rch & RM=SukeCr,Main      ,1843.4
928.0442
River Rch & RM=SukeCr,Main      ,1843.4
641.7824
River Rch & RM=SukeCr,Main      ,1514.9
1015.123
River Rch & RM=SukeCr,Main      ,1514.9
712.8068
River Rch & RM=SukeCr,Main      ,297.1
1040.612
River Rch & RM=SukeCr,Main      ,297.1
733.8632
Boundary for River Rch & Prof#=SukeCr,Main      ,1
Up Type=0
Dn Type=3
Dn Slope=0.017378

--- SukeCr.g01 (geometry) ---

Geom Title=USGS 10m DEM
Program Version=4.00

River Reach=SukeCr          ,Main
Reach XY= 30
     1750414.831      189426.283     1750406.703      189505.061
      1750493.61      189628.231     1750487.412       189854.92
     1750348.315      190155.348     1750134.103      190336.615
     1749980.923      190586.706     1749861.504      190671.737
     1749731.456      190713.002      1749480.74      190906.198
     1749281.292      190946.838     1749085.586      191182.285
     1748840.507      191238.819     1748730.466      191420.761
      1748728.59      191472.029     1748821.124      191614.581
     1748777.402      191742.291     1748670.365      191760.906
      1748635.72      191794.517     1748534.371      191923.272
     1748468.183      192087.706     1748268.147      192246.954
     1748169.636      192417.374     1747969.173      192546.535
     1747477.443      192958.482     1747339.333      193110.752
     1747109.378      193224.152     1747076.382      193294.858
     1747030.591       193307.88     1746889.535      193490.907

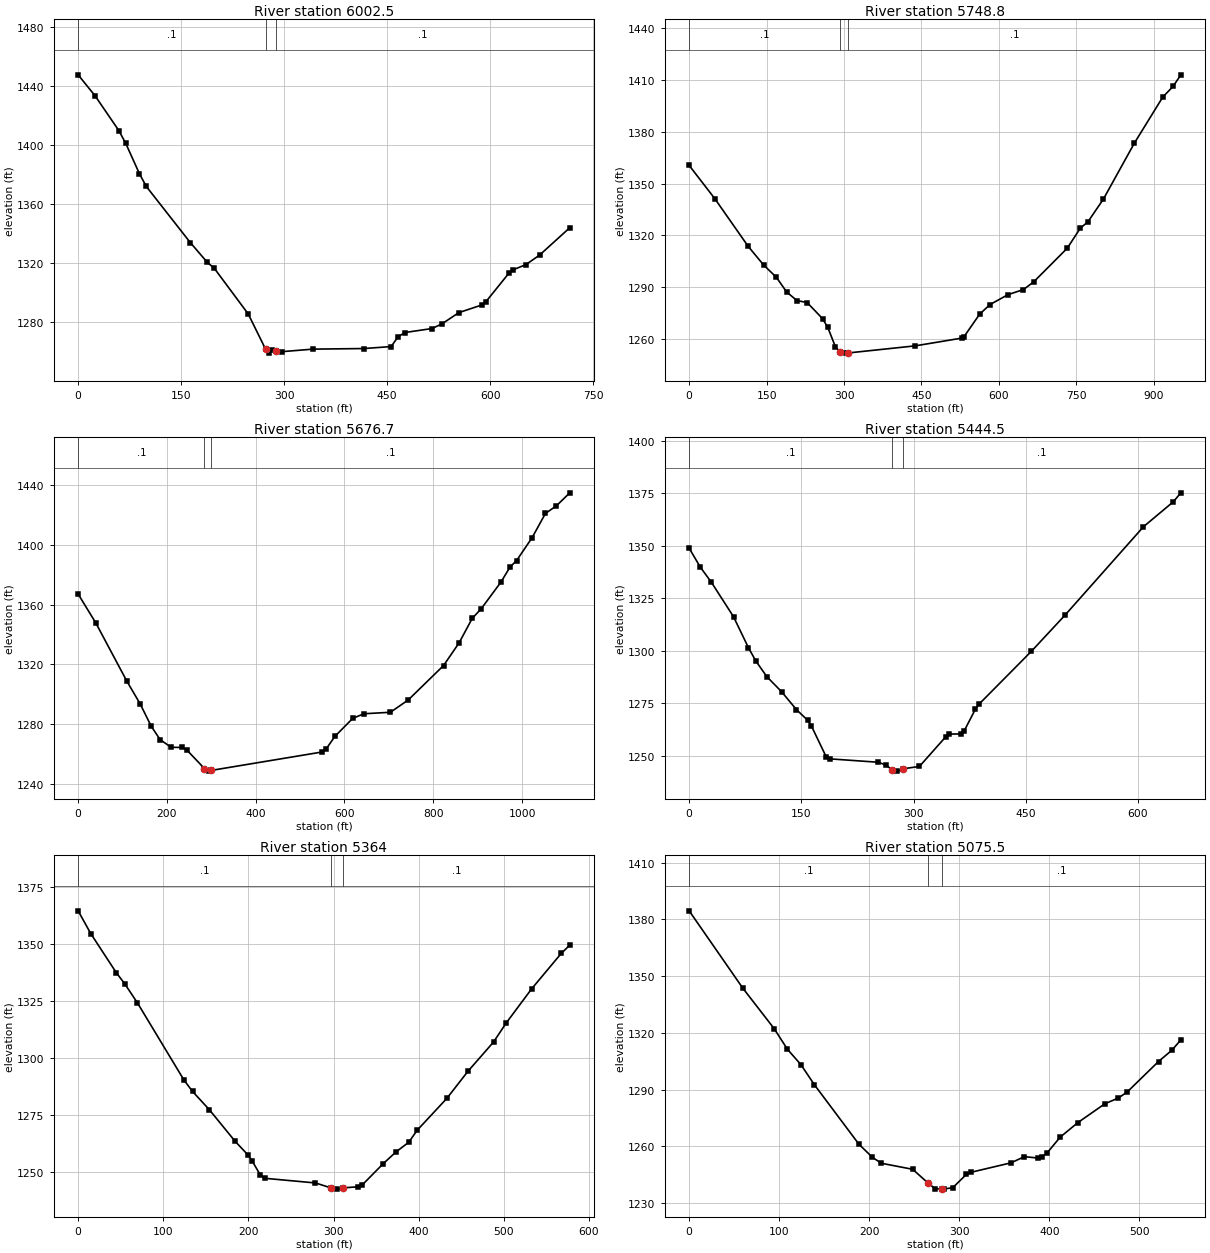
Type RM Length L Ch R = 1 ,6002.5  ,253.8,253.7,254.2
XS GIS Cut Line= 3
     1750131.595      189456.982     1750641.389       189435.21
     1750839.927      189381.647
#Sta/Elev= 30
       0 1447.77    24.8 1433.46    59.4 1409.88    69.4  1401.2    89.2 1380.76
    99.1 1372.16   163.5 1333.89   188.2 1320.52   198.2 1316.58   247.7 1285.54
     273 1261.63   277.4    1259   282.4 1260.98     288 1260.74   297.2 1260.01
   341.8 1261.71   416.1 1262.11   455.8 1263.45   465.7 1269.99   475.6 1272.97
   515.2 1275.67   529.8 1278.85   554.3 1286.46   588.6  1291.8   593.5 1293.73
   627.8 1313.54   632.7 1315.37   652.2  1319.1   671.8 1325.46   715.9 1344.07
#Mann= 3 , 0 , 0
       0      .1       0     273    .045       0     288      .1       0
Bank Sta=273,288
XS Rating Curve= 0 ,0
Exp/Cntr=0.3,0.1

Type RM Length L Ch R = 1 ,5748.8  ,75.3,72,68.8
XS GIS Cut Line= 3
     1750196.762      189665.515      1750559.53      189665.895
     1751023.386      189302.118
#Sta/Elev= 30
       0 1360.48    49.7 1341.22   114.3  1313.6   144.1 1302.82     169 1295.65
   188.8 1287.16   208.7 1282.19   228.6    1281   258.4 1271.68   268.4 1266.67
   283.3 1255.37   292.5 1252.27   303.1 1251.72   307.5  1251.8   437.7 1255.93
   527.6  1260.4   532.6 1261.34   562.6 1274.28   582.6 1279.85   617.6 1285.62
   647.5 1288.56   667.5 1293.06   732.4 1312.55   757.4 1324.04   772.4 1327.84
   802.4 1341.01   862.3 1373.41   917.3 1400.09   937.3 1406.28   952.3 1412.99
#Mann= 3 , 0 , 0
       0      .1       0   292.5    .045       0   307.5      .1       0
Bank Sta=292.5,307.5
XS Rating Curve= 0 ,0
Exp/Cntr=0.3,0.1

Type RM Length L Ch R = 1 ,5676.7  ,220,232.2,244.5
XS GIS Cut Line= 3
     1750206.661      189779.338     1750572.069      189726.571
     1751136.215      189250.181
#Sta/Elev= 30
       0 1367.07    39.9 1347.69   109.8 1308.77   139.7 1293.65   164.6 1278.72
   184.6 1269.76   209.6 1264.59   234.5  1264.5   244.5 1262.91   284.5 1250.41
   294.4 1248.67   299.5 1249.13   548.8 1261.42   558.8 1263.51   578.7 1271.98
   618.6 1283.92   643.6 1287.02   703.5 1288.01   743.4 1296.18   823.2 1319.24
   858.1 1334.36   888.1 1350.92     908 1357.18   952.9 1375.21   972.9 1385.06
   987.8 1389.46  1022.8 1404.78  1052.7 1420.92  1077.6 1426.07  1107.6 1434.71
#Mann= 3 , 0 , 0
       0      .1       0   284.5    .045       0   299.5      .1       0
Bank Sta=284.5,299.5
XS Rating Curve= 0 ,0
Exp/Cntr=0.3,0.1

Type RM Length L Ch R = 1 ,5444.5  ,80.8,80.5,80.2
XS GIS Cut Line= 4
     1750177.858      189895.277     1750344.415      189918.111
     1750615.743      190032.284     1750791.703      190115.563
#Sta/Elev= 30
       0 1348.89    14.8 1339.89    29.7 1332.62    59.3 1316.18    79.1 1301.51
      89 1295.14   103.8 1287.62   123.6  1280.4   143.4 1271.89   158.2 1266.88
   163.2 1264.23   183.1 1249.42   188.1  1248.4   252.9 1246.78   262.9 1245.47
   271.4 1243.15   277.9 1242.55   286.4 1243.69   307.8 1244.79   342.7 1258.82
   347.7  1260.2   362.7  1260.3   367.7 1261.78   382.7 1272.18   387.6 1274.54
   457.5 1299.72   502.4 1316.94   607.2 1359.09   647.2 1371.03   657.2 1375.28
#Mann= 3 , 0 , 0
       0      .1       0   271.4    .045       0   286.4      .1       0
Bank Sta=271.4,286.4
XS Rating Curve= 0 ,0
Exp/Cntr=0.3,0.1

Type RM Length L Ch R = 1 ,5364    ,277.2,288.5,299.7
XS GIS Cut Line= 2
     1750132.057      189920.385     1750667.237      190137.429
#Sta/Elev= 30
       0 1364.49    14.9 1354.47    44.8 1337.36    54.8 1332.45    69.7 1324.07
   124.5 1290.12   134.4 1285.24   154.3 1277.13   184.2 1263.44   199.1 1257.51
   204.1 1254.92   214.1  1248.5   219.1 1247.12   278.8 1245.07   296.7 1242.93
   303.7 1242.36   311.7 1242.93   328.6 1243.38   333.6 1244.15   358.5 1253.59
   373.4 1258.69   388.3 1262.92   398.3 1268.22   433.1 1282.19     458 1294.14
   487.9  1306.9   502.8 1315.26   532.7 1330.26   567.6 1345.86   577.5 1349.44
#Mann= 3 , 0 , 0
       0      .1       0   296.7    .045       0   311.7      .1       0
Bank Sta=296.7,311.7
XS Rating Curve= 0 ,0
Exp/Cntr=0.3,0.1

Type RM Length L Ch R = 1 ,5075.5  ,239.7,234,229.1
XS GIS Cut Line= 2
      1750050.45      190031.532     1750399.073      190451.761
#Sta/Elev= 30
       0 1384.55    59.6 1343.62    94.3 1322.28   109.2 1311.27   124.1 1303.18
     139 1292.59   188.6 1261.04   203.5 1254.15   213.4 1251.02   248.2 1247.82
   265.5 1240.46     273 1237.62   280.5 1237.37   282.9 1237.33   292.9 1238.16
   307.8 1245.11   312.7 1246.21   357.4 1251.24   372.3 1254.51   387.2 1253.78
   392.1 1254.56   397.1 1256.25     412 1264.83   431.8 1272.57   461.6 1282.47
   476.5  1285.5   486.4  1288.7   521.2 1304.84   536.1 1310.83     546 1316.26
#Mann= 3 , 0 , 0
       0      .1       0   265.5    .045       0   280.5      .1       0
Bank Sta=265.5,280.5
XS Rating Curve= 0 ,0
Exp/Cntr=0.3,0.1

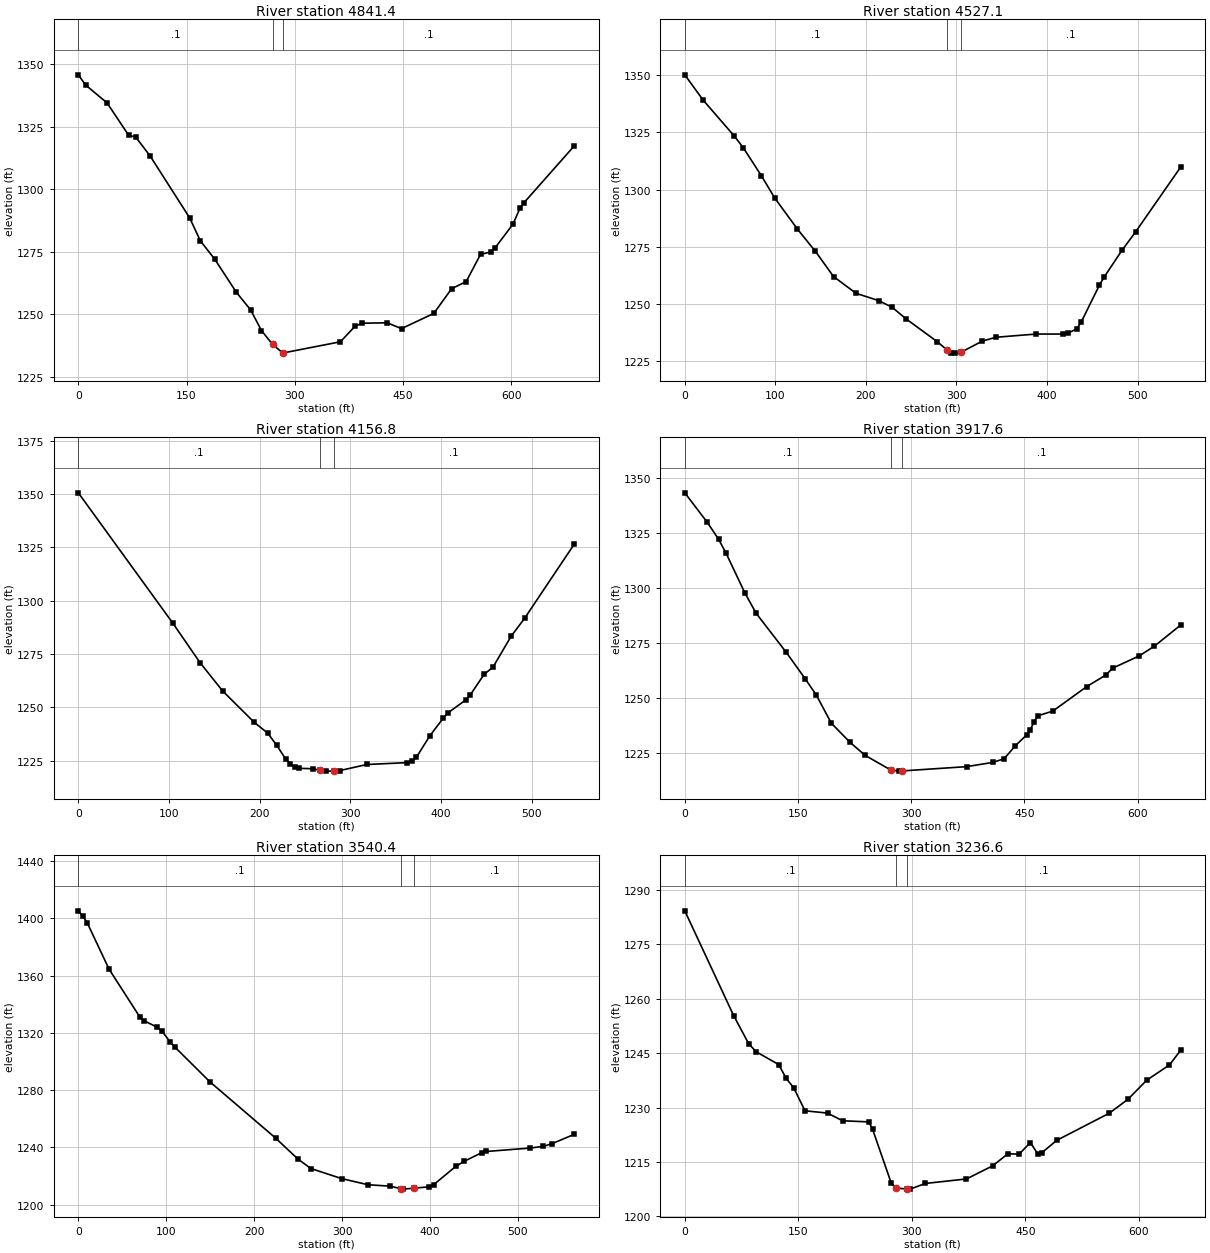
Type RM Length L Ch R = 1 ,4841.4  ,309.7,314.3,326.2
XS GIS Cut Line= 3
      1749867.11      190257.865     1750288.479      190575.164
     1750425.212      190657.805
#Sta/Elev= 30
       0 1345.78      10 1341.73    39.8 1334.56    69.7 1321.63    79.6 1320.87
    99.5 1313.34   154.3 1288.59   169.2 1279.37   189.1 1272.05     219 1258.84
   238.9 1251.76   253.8 1243.54   269.3 1237.97   283.6 1234.51   284.3 1234.61
   363.3 1239.05   383.2 1245.18   393.1 1246.47     428 1246.63   447.9 1244.31
   492.6 1250.38   517.5 1260.31   537.5  1263.1   557.4 1273.97   572.4 1275.03
   577.4 1276.52   602.4 1286.08   612.4 1292.66   617.3 1294.53   687.2 1317.33
#Mann= 3 , 0 , 0
       0      .1       0   269.3    .045       0   284.3      .1       0
Bank Sta=269.3,284.3
XS Rating Curve= 0 ,0
Exp/Cntr=0.3,0.1

Type RM Length L Ch R = 1 ,4527.1  ,367,370.3,373.6
XS GIS Cut Line= 2
     1749699.399      190421.906     1750045.421      190846.189
#Sta/Elev= 30
       0 1350.18    19.9  1339.3    54.8 1323.34    64.7 1318.23    84.6 1306.03
    99.5 1296.21   124.4 1282.73   144.3 1272.96   164.2    1262   189.1 1254.66
     214 1251.48     229 1248.54   243.9 1243.61   278.7 1233.52   289.9 1229.79
   293.6  1228.7   298.6 1228.51   304.9 1228.86   328.5 1233.77   343.4 1235.44
   388.2 1236.86   418.1 1236.84   423.1 1237.25     433 1239.18     438 1242.32
   457.9 1258.28   462.9 1261.69   482.8 1273.48   497.7 1281.47   547.5 1309.81
#Mann= 3 , 0 , 0
       0      .1       0   289.9    .045       0   304.9      .1       0
Bank Sta=289.9,304.9
XS Rating Curve= 0 ,0
Exp/Cntr=0.3,0.1

Type RM Length L Ch R = 1 ,4156.8  ,228.9,239.3,249.5
XS GIS Cut Line= 2
     1749440.924      190612.009     1749725.482      191078.909
#Sta/Elev= 30
       0 1350.58   104.4 1289.34   134.2 1270.93   159.1 1257.67   193.9 1242.96
   208.8 1237.89   218.7 1232.22   228.6 1225.76   233.6 1223.56   238.6 1222.05
   243.6 1221.37   258.5 1221.17   266.4 1220.47   273.4 1220.05   281.4 1220.09
   288.3  1220.3   318.1 1223.16   362.9 1224.03   367.8 1224.74   372.8 1226.52
   387.7 1236.65   402.6 1244.98   407.6 1247.37   427.5 1253.52   432.4 1255.88
   447.4  1265.4   457.3 1268.82   477.2 1283.25   492.1  1291.7   546.8 1326.45
#Mann= 3 , 0 , 0
       0      .1       0   266.4    .045       0   281.4      .1       0
Bank Sta=266.4,281.4
XS Rating Curve= 0 ,0
Exp/Cntr=0.3,0.1

Type RM Length L Ch R = 1 ,3917.6  ,388.8,377.2,365.7
XS GIS Cut Line= 2
     1749339.697      190656.874     1749401.485      191311.016
#Sta/Elev= 30
       0 1343.45    29.9 1329.95    44.8 1322.28    54.8 1315.85    79.6 1297.84
    94.6 1288.52   134.4 1270.79   159.3 1258.83   174.2 1251.34   194.1 1238.51
     219 1229.74   238.9 1223.85   272.9 1217.15   283.7 1216.64   287.9 1216.73
   373.3 1218.68   408.2 1220.62   423.1 1222.27     438 1228.21     453 1233.14
     458 1235.53   462.9  1239.2   467.9 1241.85   487.8 1244.02   532.6 1255.17
   557.5 1260.35   567.4 1263.64   602.3 1269.16   622.2 1273.58     657 1283.17
#Mann= 3 , 0 , 0
       0      .1       0   272.9    .045       0   287.9      .1       0
Bank Sta=272.9,287.9
XS Rating Curve= 0 ,0
Exp/Cntr=0.3,0.1

Type RM Length L Ch R = 1 ,3540.4  ,321.9,303.8,285.6
XS GIS Cut Line= 2
     1748898.108      190854.546      1749207.49      191326.058
#Sta/Elev= 30
       0 1405.16       5 1401.48      10 1396.95    34.9 1364.49    69.9 1331.08
    74.9 1328.37    89.8 1323.83    94.8 1321.44   104.8 1313.37   109.8 1310.04
   149.7 1285.75   224.6 1246.38   249.5 1231.99   264.5 1225.24   299.4 1218.22
   329.4 1213.92   354.3 1212.93   367.3 1211.13   369.3 1210.85   382.3 1211.55
   399.3 1212.46   404.2 1213.95   429.2 1226.67   439.2 1230.36   459.2 1236.41
   464.1 1237.14     514 1239.52     529 1240.71     539 1242.63     564 1249.08
#Mann= 3 , 0 , 0
       0      .1       0   367.3    .045       0   382.3      .1       0
Bank Sta=367.3,382.3
XS Rating Curve= 0 ,0
Exp/Cntr=0.3,0.1

Type RM Length L Ch R = 1 ,3236.6  ,357.3,359.8,363.1
XS GIS Cut Line= 2
      1748547.24      191202.242     1749189.649      191331.549
#Sta/Elev= 30
       0 1284.27    64.5 1255.39    84.4 1247.62    94.3 1245.39   124.1 1241.86
     134 1238.06     144 1235.42   158.9  1229.1   188.6 1228.47   208.5 1226.35
   243.2 1226.04   248.2 1223.99     273 1209.06   279.2 1207.81   294.2  1207.5
   297.9 1207.49   317.7 1209.05   372.3  1210.3   407.1 1213.94   426.9 1217.24
   441.8 1217.14   456.7 1220.33   466.6 1217.17   471.6 1217.49   491.5 1220.94
     561 1228.43   585.8  1232.3   610.6 1237.56   640.4 1241.73   655.3 1245.77
#Mann= 3 , 0 , 0
       0      .1       0   279.2    .045       0   294.2      .1       0
Bank Sta=279.2,294.2
XS Rating Curve= 0 ,0
Exp/Cntr=0.3,0.1

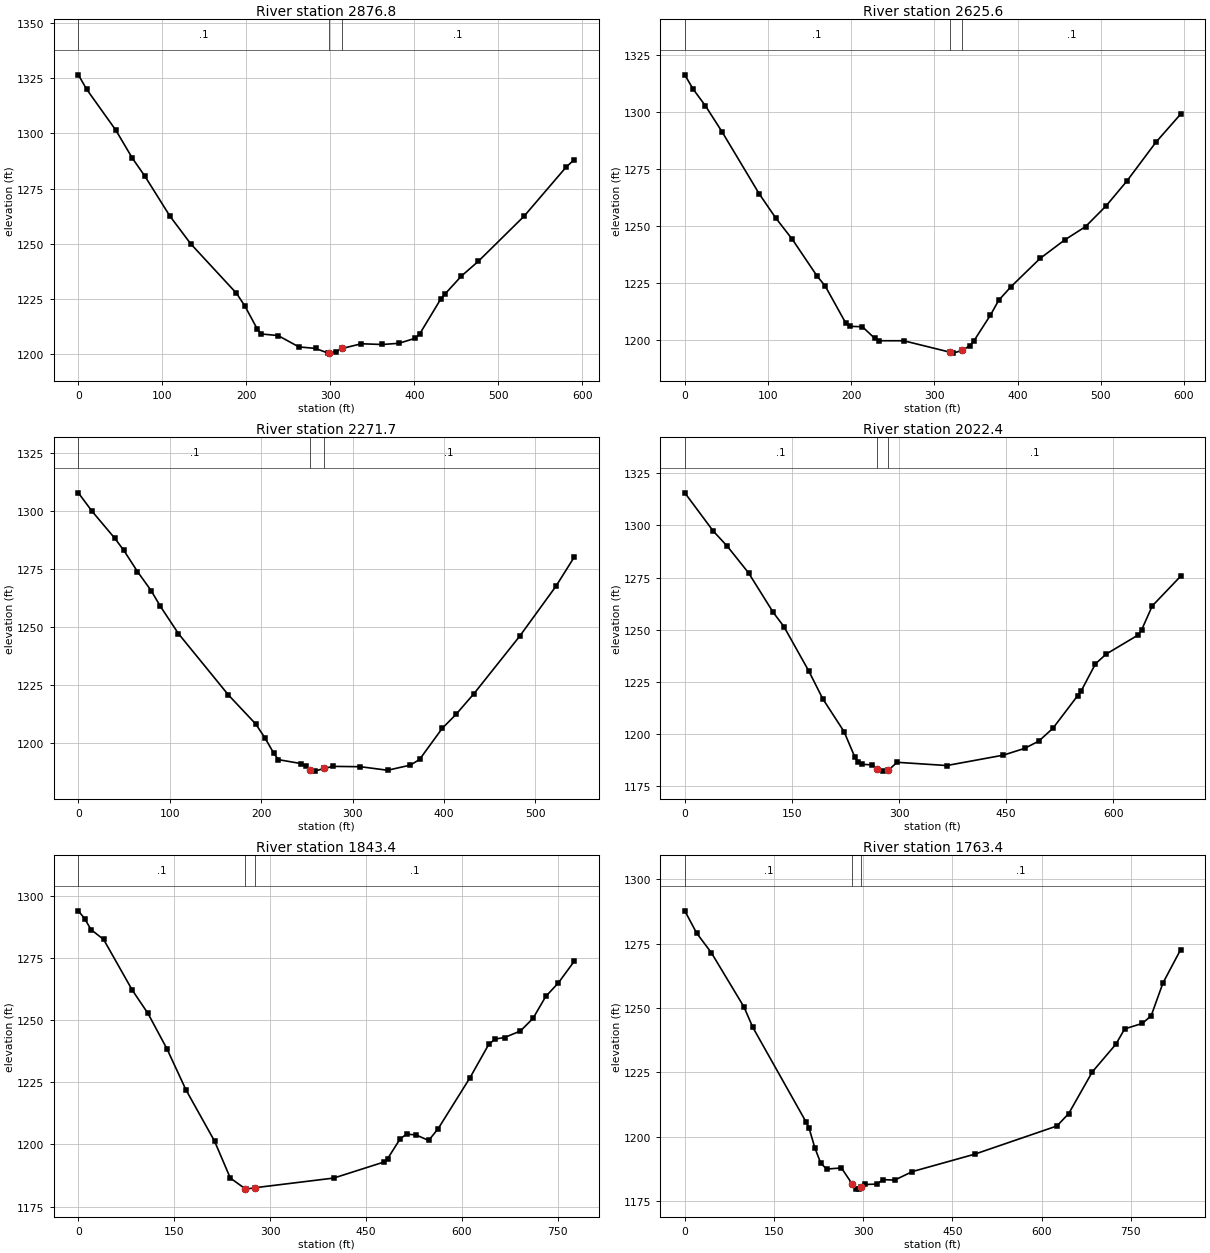
Type RM Length L Ch R = 1 ,2876.8  ,232.3,251.3,267.4
XS GIS Cut Line= 3
     1748493.108      191512.081     1748858.515      191579.822
     1749077.164      191582.946
#Sta/Elev= 30
       0 1326.51     9.9 1319.96    44.6 1301.45    64.4  1288.7    79.3 1280.55
     109 1262.53   133.8 1249.95   188.3 1227.52   198.2 1221.82   213.1  1211.3
     218 1209.09   237.8 1208.39   262.6 1203.23   282.4 1202.57   297.3 1200.42
   298.9 1200.44   307.2 1201.12   313.9 1202.52     337 1204.66   361.7 1204.33
   381.6 1204.87   401.4 1207.19   406.4 1209.12   431.3  1224.8   436.2 1227.07
   456.1 1235.35     476 1241.95   530.7 1262.47   580.4 1284.55   590.3 1288.06
#Mann= 3 , 0 , 0
       0      .1       0   298.9    .045       0   313.9      .1       0
Bank Sta=298.9,313.9
XS Rating Curve= 0 ,0
Exp/Cntr=0.3,0.1

Type RM Length L Ch R = 1 ,2625.6  ,366.4,353.9,341.4
XS GIS Cut Line= 3
     1748501.389      191530.887     1748703.437      191707.136
      1748858.92      191995.891
#Sta/Elev= 30
       0 1316.42     9.9 1310.21    24.8 1302.83    44.7 1291.48    89.4 1264.26
   109.2 1253.69   129.1 1244.35   158.9 1228.22   168.8 1223.78   193.6 1207.47
   198.6  1206.1   213.5 1205.92   228.4 1200.81   233.4 1199.79   263.2 1199.77
   318.4  1194.8   322.8 1194.35   333.4 1195.57   342.6 1197.56   347.6 1199.74
   367.5 1211.04   377.4 1217.54   392.3 1223.54   427.1 1235.87   456.9 1244.04
   481.8 1249.85   506.6 1258.97   531.5 1269.83   566.3 1286.81   596.1 1299.18
#Mann= 3 , 0 , 0
       0      .1       0   318.4    .045       0   333.4      .1       0
Bank Sta=318.4,333.4
XS Rating Curve= 0 ,0
Exp/Cntr=0.3,0.1

Type RM Length L Ch R = 1 ,2271.7  ,238.4,249.3,260.2
XS GIS Cut Line= 2
     1748276.571      191871.497     1748750.513      192135.085
#Sta/Elev= 30
       0 1307.69    14.9  1299.8    39.8 1288.14    49.8 1282.86    64.7 1273.76
    79.6 1265.57    89.6 1258.88   109.5 1247.02   164.2 1220.58     194  1208.1
     204 1202.17   213.9  1195.4   218.9 1192.73   243.8 1191.03   248.8 1190.14
   253.7 1188.22   253.7  1188.2   258.7 1187.79   268.7 1188.94   278.6 1189.84
   308.5 1189.69   338.3 1188.17   363.2 1190.39   373.2 1192.81     398 1206.22
     413  1212.2   432.8 1221.21   482.6 1245.85   522.4 1267.46   542.3 1279.95
#Mann= 3 , 0 , 0
       0      .1       0   253.7    .045       0   268.7      .1       0
Bank Sta=253.7,268.7
XS Rating Curve= 0 ,0
Exp/Cntr=0.3,0.1

Type RM Length L Ch R = 1 ,2022.4  ,190,179,168
XS GIS Cut Line= 3
     1748204.984      191953.171     1748474.564       192369.06
     1748656.006      192450.054
#Sta/Elev= 30
       0 1315.61    39.6 1297.38    59.5 1290.01    89.2 1277.27   123.9 1258.27
   138.8  1251.5   173.5 1230.28   193.3 1216.84     223 1201.17   237.9 1189.14
   242.8 1186.51   247.8 1185.52   262.7 1185.22   269.6 1183.26   277.6 1182.24
   284.6 1182.58   297.4 1186.47   366.8 1184.92   446.1  1189.9   475.8 1193.14
   495.6  1196.6   515.5 1202.79   550.3 1218.47   555.2 1220.78   575.1 1233.68
     590 1238.32   634.7 1247.45   639.7 1249.95   654.6 1261.42   694.3 1275.63
#Mann= 3 , 0 , 0
       0      .1       0   269.6    .045       0   284.6      .1       0
Bank Sta=269.6,284.6
XS Rating Curve= 0 ,0
Exp/Cntr=0.3,0.1

Type RM Length L Ch R = 1 ,1843.4  ,78.5,80,81.6
XS GIS Cut Line= 4
     1747985.746      192185.611     1748195.286      192287.358
     1748315.167      192353.847     1748685.892      192519.062
#Sta/Elev= 30
       0 1293.88     9.9 1290.74    19.8 1286.34    39.6 1282.36    84.2 1262.09
     109 1252.62   138.8 1238.35   168.5 1221.88   213.1 1201.34   237.8 1186.47
   261.3 1182.12   262.3 1182.01   276.3 1182.57   399.7 1186.46   478.9 1192.95
   483.9 1194.23   503.7 1202.24   513.6  1204.1   528.4 1203.81   548.2 1201.57
   563.1 1206.32   612.6 1226.67   642.2 1240.17   652.2 1242.34     667 1242.96
   691.8 1245.57   711.6 1250.68   731.4 1259.45   751.2 1264.91   775.9 1273.57
#Mann= 3 , 0 , 0
       0      .1       0   261.3    .045       0   276.3      .1       0
Bank Sta=261.3,276.3
XS Rating Curve= 0 ,0
Exp/Cntr=0.3,0.1

Type RM Length L Ch R = 1 ,1763.4  ,239.8,248.5,257.2
XS GIS Cut Line= 3
     1747949.748      192220.281     1748367.352       192490.14
     1748698.988      192548.108
#Sta/Elev= 30
       0  1287.7    19.9 1279.07    44.8 1271.37    99.4 1250.42   114.4 1242.44
   203.9 1205.71   208.8 1203.46   218.8  1195.6   228.7 1189.64   238.7 1187.41
   263.5 1187.83   281.4 1181.63   288.4 1179.68   293.4 1179.61   296.4 1180.28
   303.3 1181.42   323.2 1181.56   333.1  1183.3     353 1183.12   382.8 1186.43
   487.3 1193.16   625.9 1204.14   645.7 1208.97   685.4 1225.15     725 1235.89
   739.8 1241.84   769.5 1243.98   784.4 1246.96   804.2 1259.68   833.9 1272.61
#Mann= 3 , 0 , 0
       0      .1       0   281.4    .045       0   296.4      .1       0
Bank Sta=281.4,296.4
XS Rating Curve= 0 ,0
Exp/Cntr=0.3,0.1

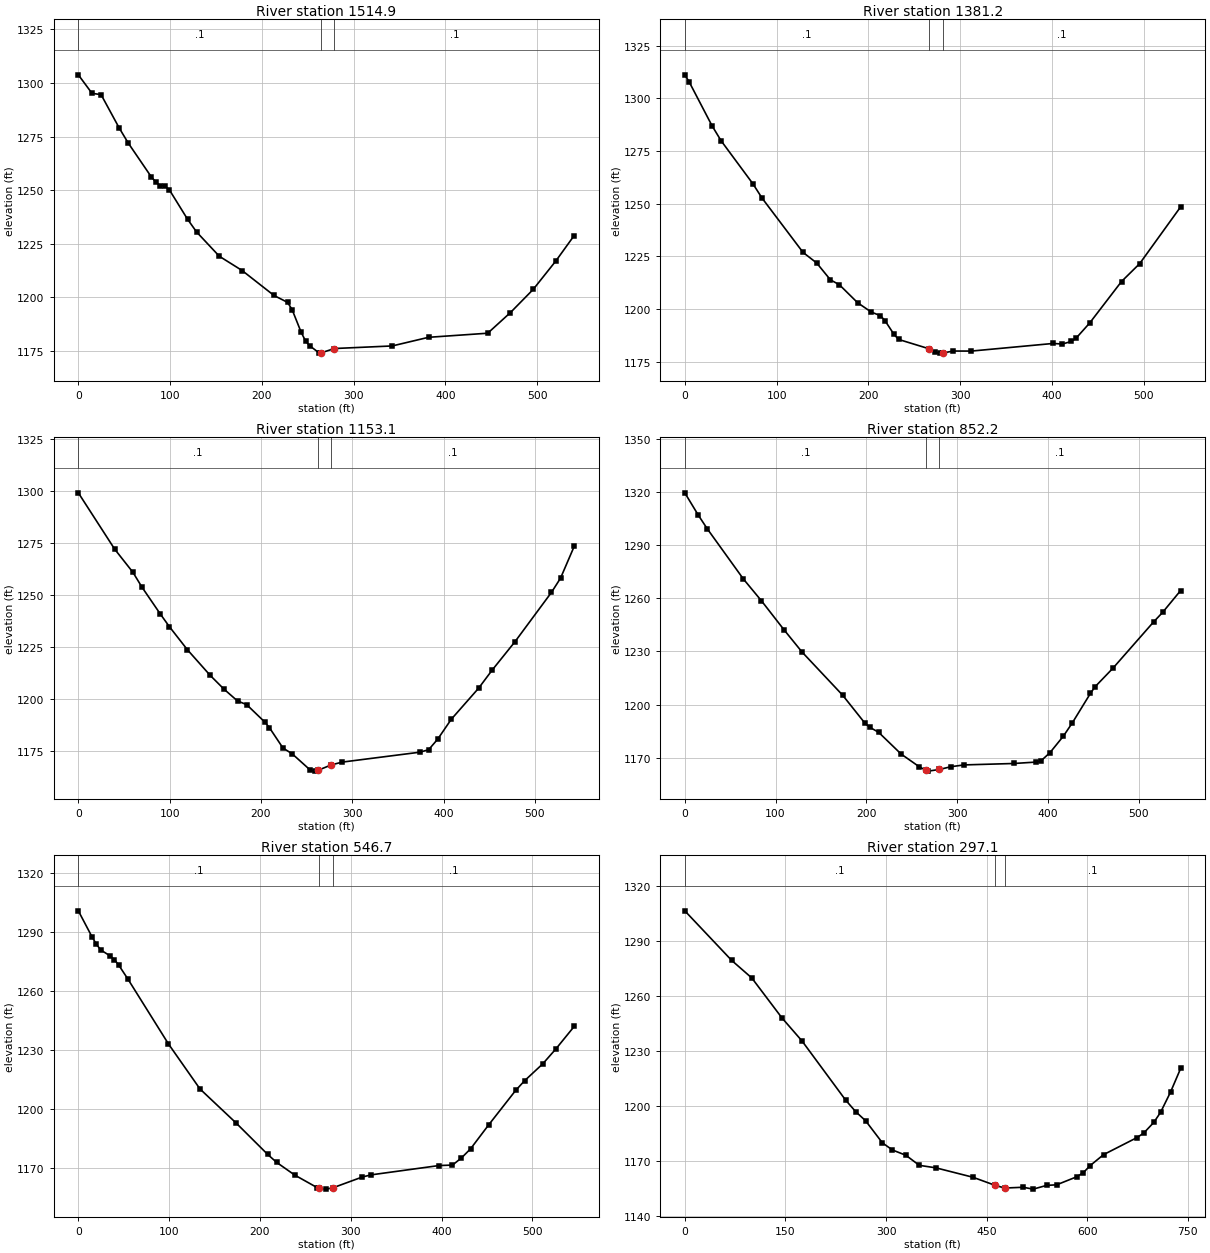
Type RM Length L Ch R = 1 ,1514.9  ,134.6,133.7,132.8
XS GIS Cut Line= 2
     1747850.082      192299.615     1748153.975      192746.423
#Sta/Elev= 30
       0 1303.78    14.9 1295.15    24.8 1294.54    44.6 1278.94    54.5 1271.89
    79.3 1256.32    84.3 1253.81    89.2 1252.14    94.2 1251.98    99.2 1250.14
     119 1236.44   128.9 1230.46   153.7 1219.13   178.5 1212.49   213.2 1200.86
     228 1197.64     233 1194.25   242.9 1183.63   247.9 1179.41   252.8 1177.18
   262.7 1173.95   264.1 1174.01   279.1  1176.1   342.1  1177.3   381.7 1181.33
   446.2 1183.24     471 1192.89   495.7 1203.65   520.5 1216.98   540.4 1228.79
#Mann= 3 , 0 , 0
       0      .1       0   264.1    .045       0   279.1      .1       0
Bank Sta=264.1,279.1
XS Rating Curve= 0 ,0
Exp/Cntr=0.3,0.1

Type RM Length L Ch R = 1 ,1381.2  ,229.8,228.1,226.3
XS GIS Cut Line= 2
     1747743.969      192395.151     1748065.331      192829.342
#Sta/Elev= 30
       0 1311.09       5 1307.54    29.7 1286.91    39.6 1279.79    74.3 1259.35
    84.2  1252.6   128.8 1226.88   143.7 1221.84   158.6 1213.88   168.5 1211.49
   188.3 1202.99   203.2 1198.56   213.1 1196.85     218 1194.56     228 1187.93
   232.9 1185.59   265.8  1181.2   272.6 1179.44   277.5 1179.09   280.8 1179.12
   292.4 1180.08   312.2 1180.06   401.4 1183.68   411.3  1183.4   421.2 1184.64
   426.2 1186.13   441.1 1193.37   475.8 1213.06   495.6 1221.54   540.2 1248.46
#Mann= 3 , 0 , 0
       0      .1       0   265.8    .045       0   280.8      .1       0
Bank Sta=265.8,280.8
XS Rating Curve= 0 ,0
Exp/Cntr=0.3,0.1

Type RM Length L Ch R = 1 ,1153.1  ,298.3,300.9,303.5
XS GIS Cut Line= 2
     1747557.263      192558.854     1747912.753      192969.188
#Sta/Elev= 30
       0 1299.05    39.8 1271.94    59.8 1260.79    69.7 1253.64    89.6 1240.85
    99.6  1234.7   119.5 1223.51   144.4  1211.2   159.4 1204.62   174.3  1198.9
   184.3 1197.14   204.2 1188.74   209.2 1186.06   224.1 1176.24   234.1 1173.49
     254 1165.63     259 1165.14     262 1165.46     277 1168.14   288.9 1169.48
   373.6 1174.23   383.5 1175.42   393.5 1180.53   408.4 1190.12   438.3 1205.05
   453.2  1213.8   478.2 1227.47     518 1251.12     528    1258   542.9 1273.25
#Mann= 3 , 0 , 0
       0      .1       0     262    .045       0     277      .1       0
Bank Sta=262,277
XS Rating Curve= 0 ,0
Exp/Cntr=0.3,0.1

Type RM Length L Ch R = 1 ,852.2   ,307.6,305.5,303.4
XS GIS Cut Line= 2
     1747343.212      192720.279     1747651.174      193171.356
#Sta/Elev= 30
       0  1319.5    14.9 1306.88    24.8 1299.16    64.6 1270.84    84.4  1258.6
   109.2 1242.28   129.1 1229.71   173.8 1205.36   198.6 1189.42   203.6 1187.27
   213.5 1184.38   238.3 1172.11   258.2 1164.96   265.5 1162.97   268.1 1162.47
   280.5  1163.4     293 1164.95   307.8 1165.98   362.5 1166.78   387.3 1167.59
   392.3 1168.24   402.2 1172.85   417.1 1182.25     427 1189.78   446.9 1206.39
   451.8 1209.99   471.7 1220.58   516.4 1246.65   526.3    1252   546.2 1264.36
#Mann= 3 , 0 , 0
       0      .1       0   265.5    .045       0   280.5      .1       0
Bank Sta=265.5,280.5
XS Rating Curve= 0 ,0
Exp/Cntr=0.3,0.1

Type RM Length L Ch R = 1 ,546.7   ,250.7,249.6,248.2
XS GIS Cut Line= 2
     1747098.662      192936.343     1747447.957      193356.176
#Sta/Elev= 30
       0 1300.79    14.9 1287.74    19.9 1283.78    24.8 1280.91    34.8 1277.95
    39.7 1276.06    44.7 1273.09    54.6 1266.14    99.3 1233.19     134 1210.35
   173.8 1193.06   208.5 1177.15   218.4 1173.08   238.3 1166.65   263.1 1160.25
   265.6 1159.92   273.1  1159.5   280.6 1160.21   312.8 1165.66   322.7 1166.76
   397.2 1171.47   412.1 1171.71     422 1175.36     432 1179.96   451.8 1192.04
   481.6 1209.58   491.5 1214.53   511.4 1223.05   526.3 1230.86   546.1 1242.08
#Mann= 3 , 0 , 0
       0      .1       0   265.6    .045       0   280.6      .1       0
Bank Sta=265.6,280.6
XS Rating Curve= 0 ,0
Exp/Cntr=0.3,0.1

Type RM Length L Ch R = 1 ,297.1   ,169.6,163.2,157
XS GIS Cut Line= 3
     1746955.507      192844.957     1747017.294      193214.338
     1747272.579      193474.768
#Sta/Elev= 30
       0 1306.57    69.9 1279.48    99.9 1269.88   144.8 1248.09   174.8 1235.45
   239.7 1203.19   254.7 1196.88   269.6 1191.85   294.6  1179.8   309.6  1175.9
   329.6 1173.02   349.6 1167.52   374.5 1166.14   429.5 1161.02   461.9 1156.69
   476.9 1155.11   504.4 1155.54   519.4 1154.52   539.4 1156.56   554.4 1156.88
   584.3 1161.26   594.3 1163.56   604.3 1167.37   624.3 1173.36   674.2 1182.69
   684.2 1185.15   699.2 1190.98   709.2 1196.41   724.2 1207.58   739.2 1220.44
#Mann= 3 , 0 , 0
       0      .1       0   461.9    .045       0   476.9      .1       0
Bank Sta=461.9,476.9
XS Rating Curve= 0 ,0
Exp/Cntr=0.3,0.1

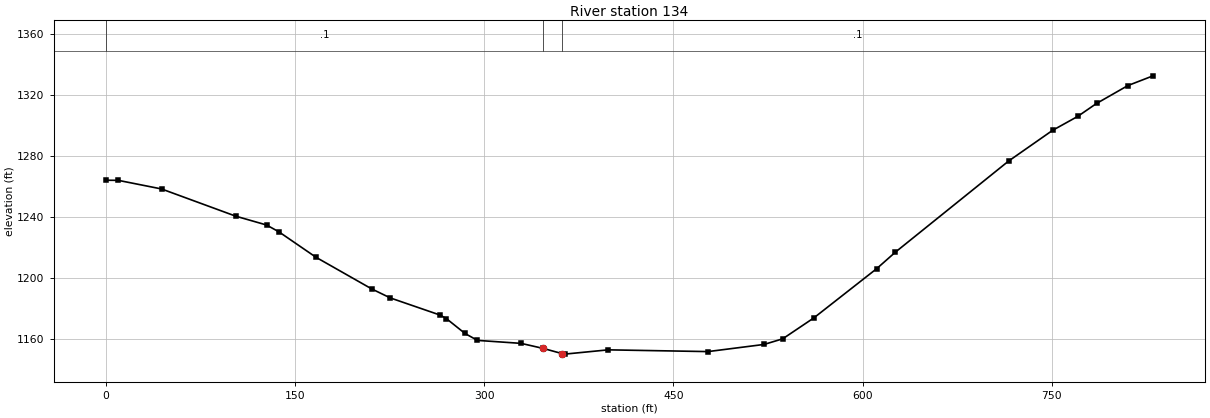
Type RM Length L Ch R = 1 ,134     ,125.1,134,142.8
XS GIS Cut Line= 4
     1746675.449       193208.63     1746871.557      193329.518
     1747150.944      193497.419     1747380.632      193646.515
#Sta/Elev= 30
       0 1264.25     9.8 1264.18    44.1 1258.54   102.9 1240.71   127.4  1234.9
   137.2 1230.41   166.6 1213.74   210.8 1192.99   225.5  1187.1     265 1175.86
   269.9 1173.59   284.7  1163.8   294.6 1159.27   329.2 1157.32   346.8 1153.99
   361.8 1150.59   363.7 1150.27   398.3 1153.08   477.3 1151.93   521.8 1156.62
   536.6 1160.31   561.3 1174.03   611.1 1206.29     626 1217.17   715.6 1276.78
   750.5 1296.93   770.4 1306.06   785.4 1314.58   810.2 1326.29   830.2 1332.69
#Mann= 3 , 0 , 0
       0      .1       0   346.8    .045       0   361.8      .1       0
Bank Sta=346.8,361.8
XS Rating Curve= 0 ,0
Exp/Cntr=0.3,0.1

Chan Stop Cuts=-1
Use User Specified Reach Order=0